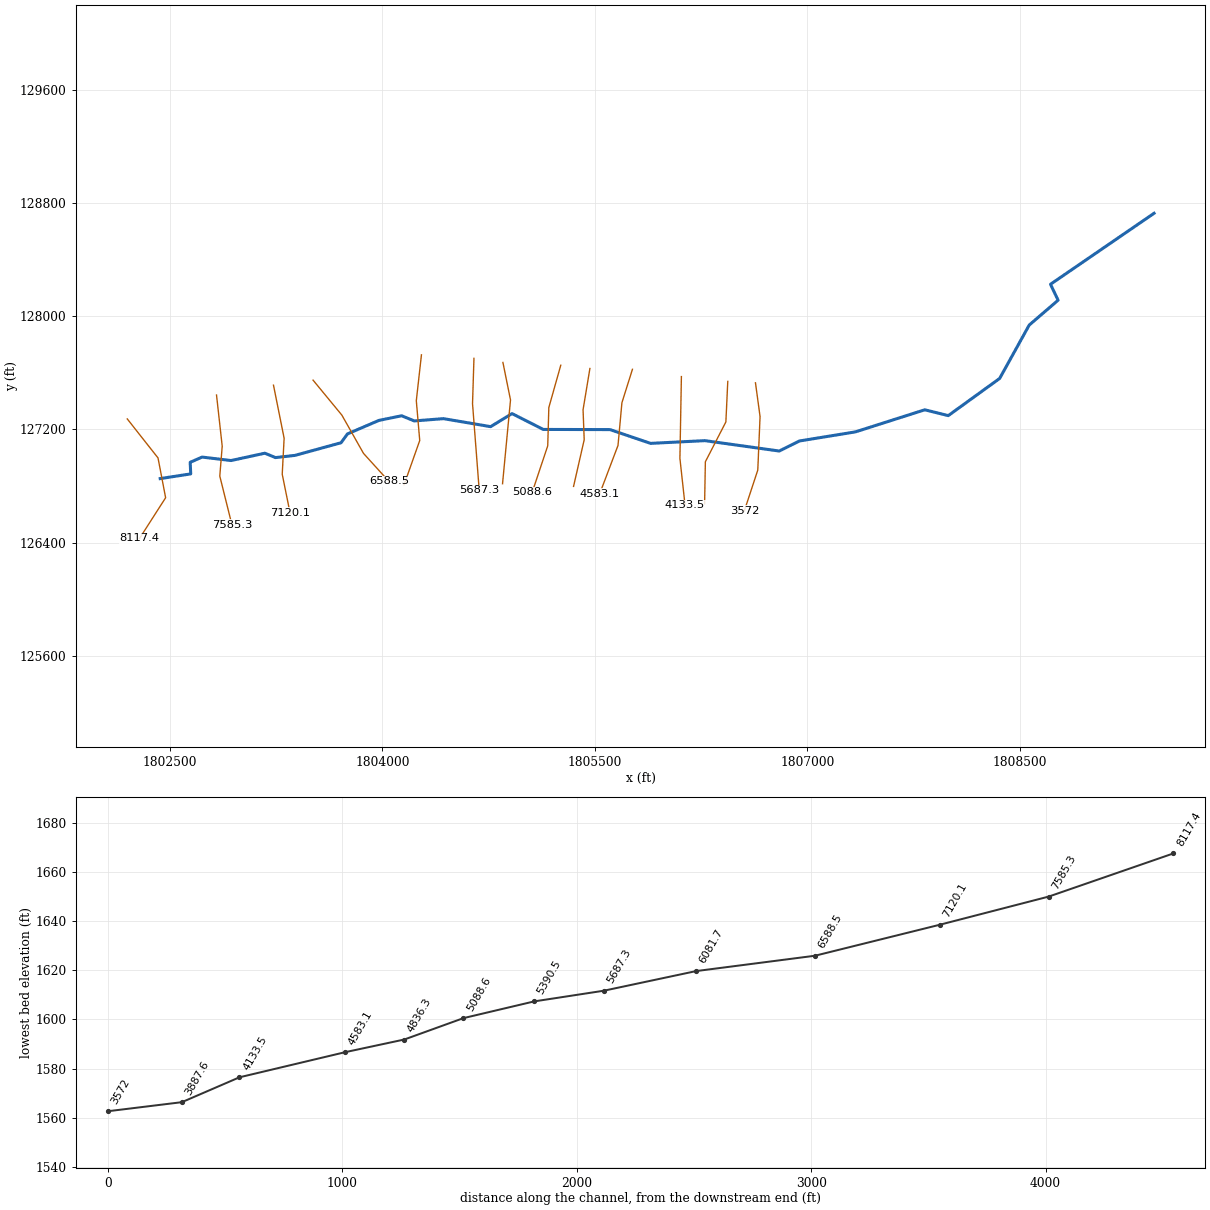
--- Right Fork Sandlick Creek.prj (project) ---

Proj Title=Right Fork Sandlick Creek
Current Plan=p01
Default Exp/Contr=0,0
English Units
Geom File=g01
Flow File=f01
Plan File=p01
BEGIN DESCRIPTION:
END DESCRIPTION:
DSS Export Rating Curves= 0
DSS Export Rating Curve Sorted= 0
DSS Export Volume Flow Curves= 0
DXF OffsetX= 0
DXF OffsetY= 0
DXF ScaleX= 0
DXF ScaleY= 0

--- Right Fork Sandlick Creek.p01 (plan) ---

Plan Title=Floodplain
Program Version=4.00
Geom File=g01
Flow File=f01
K Sum by GR=0
Std Step Tol=0.01
Critical Tol=0.01
Num of Std Step Trials=20
Max Error Tol=0.3
Flow Tol Ratio=0.001
Split Flow NTrial=30
Split Flow Tol=0.02
Split Flow Ratio=0.02
Log Output Level=0
Friction Slope Method=1
Unsteady Friction Slope Method=2
Unsteady Bridges Friction Slope Method=1
Global Log Level=0
CheckData=False
Run HTab=0
Run UNet=0
Run PostProcess=0
UNET Theta=0
UNET Theta Warmup=0
UNET ZTol=0
UNET ZSATol=0
UNET MxIter=0
UNET MaxInSteps=0
UNET DtIC=0
UNET DtMin=0
UNET MaxCRTS=0
UNET WFStab=0
UNET SFStab=0
UNET WFX=0
UNET SFX=0
UNET DSS MLevel=0
UNET DZMax Abort=0
UNET Convert EG Bridges=0
UNET Use Existing IB Tables=0
UNET Froude Limit=0
UNET Froude Power=0
Write IC File=0
Echo Input=False
Echo Output=False
Write Detailed=0

--- Right Fork Sandlick Creek.f01 (steady flow) ---

Flow Title=NFF Regression Equation
Program Version=4.00
Number of Profiles=1
Profile Names=P100yr
River Rch & RM=Right Fork Sa...,Main      ,8117.4
594.8649
River Rch & RM=Right Fork Sa...,Main      ,6588.5
631.4563
River Rch & RM=Right Fork Sa...,Main      ,5687.3
696.1279
River Rch & RM=Right Fork Sa...,Main      ,5390.5
719.8299
River Rch & RM=Right Fork Sa...,Main      ,4133.5
791.8051
Boundary for River Rch & Prof#=Right Fork Sa...,Main      ,1
Up Type=0
Dn Type=3
Dn Slope=0.025225

--- Right Fork Sandlick Creek.g01 (geometry) ---

Geom Title=USGS 10m DEM
Program Version=4.00

River Reach=Right Fork Sa...,Main
Reach XY= 30
      1802431.07      126852.593      1802646.42      126885.802
     1802642.751      126967.753     1802726.828      127004.723
     1802931.356      126980.275     1803169.873      127032.153
     1803244.409      127001.145     1803382.152      127016.649
     1803707.727      127106.093     1803753.046      127168.703
     1803974.866       127264.11     1804135.269      127296.906
     1804224.925      127260.397     1804430.433      127276.632
     1804763.761      127219.984     1804914.622      127312.409
      1805135.25      127200.307     1805606.321      127199.114
     1805892.755       127101.71     1806275.956         127121.
     1806800.722      127047.573     1806944.079      127118.702
     1807339.146      127183.015     1807828.385      127339.204
     1807994.469      127298.099     1808357.015      127561.063
     1808565.717      127938.516     1808769.648      128114.422
     1808715.982      128227.121      1809447.16      128729.382

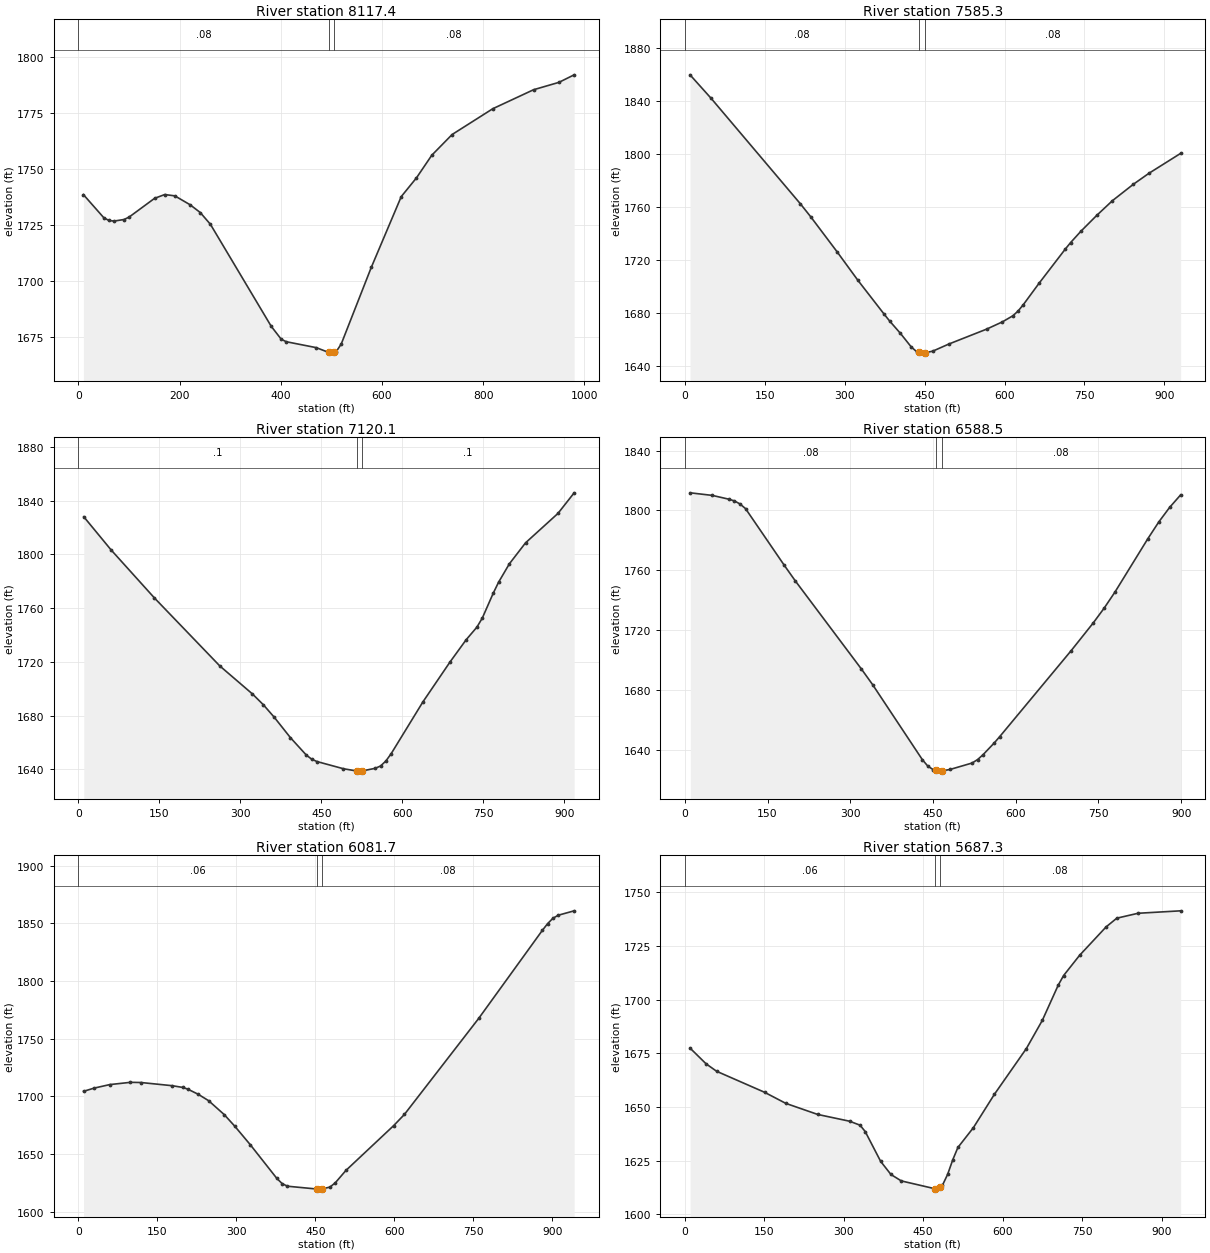
Type RM Length L Ch R = 1 ,8117.4  ,535.1,532.1,524.1
XS GIS Cut Line= 4
     1802198.424      127274.763     1802415.619      126998.577
     1802469.247      126717.029     1802285.038      126429.261
#Sta/Elev= 30
      10 1738.59    50.2 1728.26    60.2 1727.03    70.3 1726.73    90.3 1727.44
   100.4 1728.54   150.6 1736.91   170.7 1738.61   190.7 1738.02   220.9 1734.03
   240.9 1730.56     261 1725.28     381 1679.68   400.8 1673.88   410.7 1672.75
     470  1670.1   494.6 1667.96   499.6 1667.64   504.6 1667.98   509.5 1668.31
   519.4 1671.71   578.7 1705.97     638  1737.7   668.1 1746.09   698.3  1756.2
   738.5 1765.48   818.9 1777.03   899.3 1785.51   949.5 1788.82   979.6 1792.19
#Mann= 3 , 0 , 0
       0     .08       0   494.6    .045       0   504.6     .08       0
Bank Sta=494.6,504.6
XS Rating Curve= 0 ,0
Exp/Cntr=0.3,0.1

Type RM Length L Ch R = 1 ,7585.3  ,465.7,465.2,464.7
XS GIS Cut Line= 4
     1802828.557      127443.692     1802868.778      127081.701
     1802851.621       126870.27     1802937.074      126526.705
#Sta/Elev= 30
     9.8 1859.94    49.2  1842.3   216.6  1762.8   236.3 1752.88   285.5 1726.62
   324.8 1704.98   374.3 1679.32   384.4 1674.25   404.6 1664.96   424.8 1654.77
   434.9 1651.21     440 1650.63     445 1650.05     450 1650.26   465.2 1651.52
   495.5 1656.91   566.2 1668.12     596 1673.63   615.7 1678.24   625.5 1681.85
   635.4 1686.69   664.9 1702.82     714 1728.53   723.9 1733.39   743.5 1742.06
     773 1753.93   802.5 1765.04   841.9 1777.46   871.4  1785.8   930.4  1800.7
#Mann= 3 , 0 , 0
       0     .08       0     440    .045       0     450     .08       0
Bank Sta=440,450
XS Rating Curve= 0 ,0
Exp/Cntr=0.3,0.1

Type RM Length L Ch R = 1 ,7120.1  ,519.4,531.6,543.7
XS GIS Cut Line= 4
      1803230.77      127513.409     1803305.849      127138.011
     1803292.442      126883.276     1803347.856      126608.849
#Sta/Elev= 30
    10.1 1828.11    60.4 1803.53     141 1767.56   261.9 1716.95   322.4 1696.04
   342.5 1688.03   362.7 1678.71   392.6 1663.52   422.1 1650.51   431.9 1647.49
   441.7 1645.71   490.8 1640.34   515.2 1638.67   520.2 1638.56   525.2 1638.68
   549.6 1640.66   559.4 1642.37   569.2 1646.04   579.1 1651.54   637.9 1690.16
   687.9 1719.79   717.9 1736.44   737.9 1745.88   747.9 1752.66   767.9 1770.99
   777.9 1779.28   797.9 1793.02   827.9 1808.69   887.9 1830.61   917.9 1845.96
#Mann= 3 , 0 , 0
       0      .1       0   515.2    .045       0   525.2      .1       0
Bank Sta=515.2,525.2
XS Rating Curve= 0 ,0
Exp/Cntr=0.3,0.1

Type RM Length L Ch R = 1 ,6588.5  ,511.7,506.8,499.3
XS GIS Cut Line= 4
     1803510.036      127549.021     1803713.424      127301.577
     1803866.265      127030.754      1804045.92       126832.33
#Sta/Elev= 30
      10 1811.75      50 1810.02    80.1 1807.48    90.1 1806.33   100.1 1804.31
   110.1 1801.22   180.2 1763.46   200.2 1753.04   320.3 1694.08   340.4 1683.77
   430.7 1633.61   440.7 1629.27   450.7 1626.86   455.7 1626.41   460.7 1625.95
   465.7 1626.08   480.8 1627.05   520.9 1631.36     531 1633.69     541    1637
   561.1 1644.79   571.1 1649.03   700.7 1706.46   740.3 1724.77   760.2 1734.69
     780 1745.53   839.5 1781.09   859.3 1792.25   879.1 1802.04     899 1810.37
#Mann= 3 , 0 , 0
       0     .08       0   455.7    .045       0   465.7     .08       0
Bank Sta=455.7,465.7
XS Rating Curve= 0 ,0
Exp/Cntr=0.3,0.1

Type RM Length L Ch R = 1 ,6081.7  ,396,394.4,392.7
XS GIS Cut Line= 4
     1804275.211      127727.912     1804238.982      127403.471
     1804263.115      127121.922     1804152.544      126808.452
#Sta/Elev= 30
     9.9 1704.41    29.7 1707.17    59.4 1710.23    98.9 1712.21   118.7 1712.06
   178.1  1709.3   197.9 1707.82   207.7 1706.34   227.5 1701.89   247.3 1696.33
     277 1684.26   296.8 1674.33   326.5 1658.16   376.9    1629     387 1624.48
   397.1 1622.22   452.7 1619.79   457.7  1619.7   462.7 1619.86   477.8 1621.48
   487.9  1625.2   508.1 1635.91   598.9 1674.79   619.1  1684.4   760.1 1767.55
     881 1843.85   891.1 1849.71   901.1 1854.32   911.2 1856.96   941.4 1860.77
#Mann= 3 , 0 , 0
       0     .06       0   452.7    .045       0   462.7     .08       0
Bank Sta=452.7,462.7
XS Rating Curve= 0 ,0
Exp/Cntr=0.3,0.1

Type RM Length L Ch R = 1 ,5687.3  ,296.7,296.8,297
XS GIS Cut Line= 3
     1804645.866       127703.07     1804635.831       127382.02
     1804683.086       126770.08
#Sta/Elev= 30
      10 1677.39    40.2 1670.08    60.2 1666.59   150.6 1656.82   190.7 1651.65
   250.9 1646.49   311.2 1643.33   330.9 1641.48   340.6 1638.52   369.8 1624.62
   389.2 1618.51   408.7 1615.52   471.7  1611.9   476.7 1611.69   481.7 1612.61
   486.4 1613.47   496.2 1618.55   505.9 1625.35   515.6  1631.1   544.8 1640.31
   584.6 1655.91   644.9 1677.21     675 1690.33   705.1 1706.78   715.2 1711.23
   745.3 1720.62   795.5  1733.9   815.6 1737.94   855.7 1740.23   936.1 1741.37
#Mann= 3 , 0 , 0
       0     .06       0   471.7    .045       0   481.7     .08       0
Bank Sta=471.7,481.7
XS Rating Curve= 0 ,0
Exp/Cntr=0.3,0.1

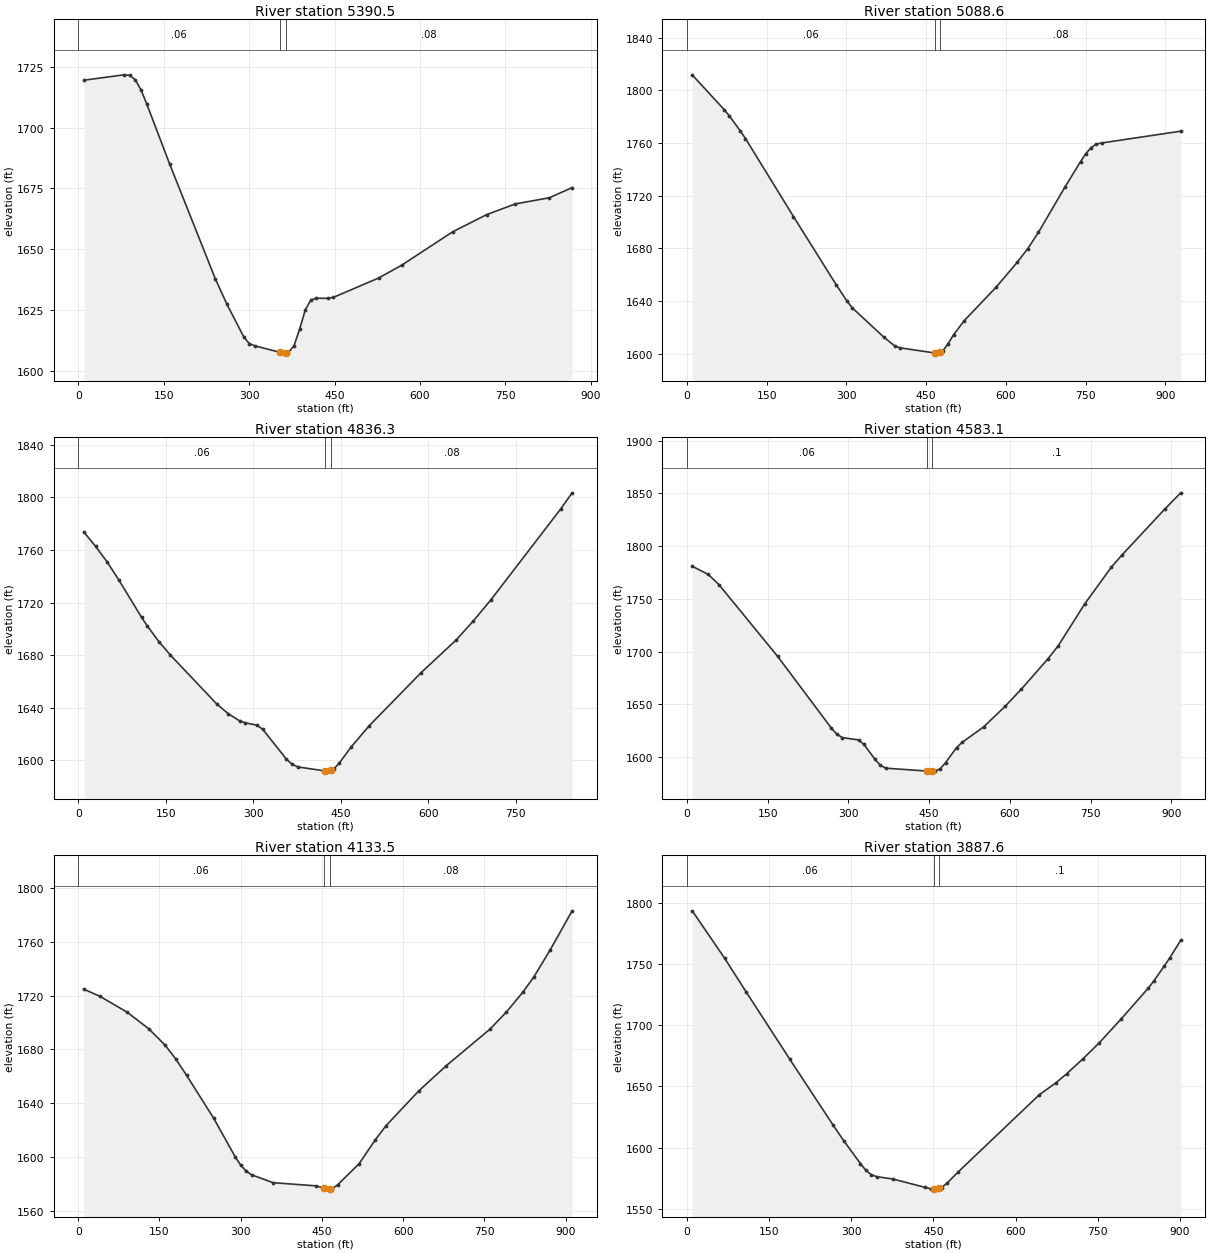
Type RM Length L Ch R = 1 ,5390.5  ,302.4,301.9,301.4
XS GIS Cut Line= 3
     1804850.345      127674.294     1804903.973      127408.834
     1804847.663      126816.241
#Sta/Elev= 30
      10 1719.45    80.2 1721.65    90.3 1721.44   100.3 1719.62   110.3 1715.39
   120.4 1709.63   160.5 1685.03   240.7 1637.86   260.8 1627.55   290.5 1614.06
   300.3 1611.24   310.2 1610.34   354.3 1607.67   359.3 1607.34   364.3 1607.46
   369.1 1607.57     379 1610.47   388.8 1617.22   398.6 1625.05   408.5 1629.24
   418.3 1629.87     438 1629.86   447.8 1630.22   527.7 1638.22   567.6 1643.42
   657.5 1657.18   717.4 1664.26   767.4 1668.62   827.3 1671.17   867.2 1675.32
#Mann= 3 , 0 , 0
       0     .06       0   354.3    .045       0   364.3     .08       0
Bank Sta=354.3,364.3
XS Rating Curve= 0 ,0
Exp/Cntr=0.3,0.1

Type RM Length L Ch R = 1 ,5088.6  ,250.9,252.2,253.6
XS GIS Cut Line= 4
     1805258.808      127654.539     1805174.496       127355.29
     1805166.752      127084.383     1805056.899      126755.253
#Sta/Elev= 30
      10 1811.84    70.2 1785.45    80.2 1780.51   100.3 1769.41   110.3 1763.48
   200.6 1704.22   280.8 1652.55   300.9 1640.22   310.9 1635.01   371.1 1612.43
   391.2 1605.93   401.2 1604.52   466.5 1600.63   471.5 1600.52   476.5 1601.35
   481.5 1602.18   491.6 1607.81   501.6  1614.4   521.7 1625.16   581.9 1650.67
   621.6 1669.59   641.4 1679.95   661.2 1692.13   710.8 1726.37   740.5 1745.96
   750.4 1751.96   760.4 1756.63   770.3 1759.26   780.2 1760.09   928.9 1769.05
#Mann= 3 , 0 , 0
       0     .06       0   466.5    .045       0   476.5     .08       0
Bank Sta=466.5,476.5
XS Rating Curve= 0 ,0
Exp/Cntr=0.3,0.1

Type RM Length L Ch R = 1 ,4836.3  ,255.8,253.2,250.6
XS GIS Cut Line= 4
     1805464.389      127631.391     1805416.123      127339.117
     1805424.167      127127.285     1805349.088      126797.471
#Sta/Elev= 30
     9.9 1773.51    29.6 1762.77    49.4 1750.99    69.1  1737.5   108.6 1708.73
   118.5 1702.14   138.2 1690.29     158 1680.05     237 1643.07   256.7 1635.62
   276.5 1630.07   286.4 1628.52   306.3 1626.77   316.4  1623.5   356.8  1600.9
   366.9 1596.94     377 1594.95   422.5 1592.01   427.5 1591.81   432.5 1592.51
   437.6 1593.23   447.7 1598.12   467.8 1610.19   498.1 1626.03   587.8 1666.78
   647.5 1691.42   677.3  1706.1   707.2 1722.01   826.6    1791   846.5 1803.43
#Mann= 3 , 0 , 0
       0     .06       0   422.5    .045       0   432.5     .08       0
Bank Sta=422.5,432.5
XS Rating Curve= 0 ,0
Exp/Cntr=0.3,0.1

Type RM Length L Ch R = 1 ,4583.1  ,448.6,449.7,450.8
XS GIS Cut Line= 4
     1805764.785      127625.836      1805690.35      127388.994
     1805662.814      127087.064     1805533.449      126744.876
#Sta/Elev= 30
     9.9  1780.9    39.7 1773.13    59.6 1763.47   168.8 1695.32   268.5  1627.4
   278.6 1621.66   288.7 1618.42     319  1616.2   329.1 1611.93   349.3 1597.91
   359.4 1592.22   369.5 1589.43   445.4 1586.73   450.4 1586.63   455.4 1586.64
   460.5 1586.65   470.6 1588.92   480.7 1594.71   500.9 1608.91     511 1613.78
   551.4 1628.61     591 1647.99   620.7 1664.02   670.1 1692.71   689.9 1705.51
   739.3 1745.43   788.7 1780.13   808.5 1791.71   887.6 1835.02   917.3 1850.47
#Mann= 3 , 0 , 0
       0     .06       0   445.4    .045       0   455.4      .1       0
Bank Sta=445.4,455.4
XS Rating Curve= 0 ,0
Exp/Cntr=0.3,0.1

Type RM Length L Ch R = 1 ,4133.5  ,254.6,245.8,237.1
XS GIS Cut Line= 3
     1806110.318      127574.093     1806099.884      126995.896
     1806136.022      126664.268
#Sta/Elev= 30
      10 1724.76      40 1719.45      90 1707.73     130 1695.43     160 1683.42
     180 1673.01     200 1660.87     250 1629.06   290.1 1600.19   300.1 1594.18
   310.1 1589.82     320 1587.05   359.7 1581.22   439.3 1578.82   454.1 1577.15
   459.1 1576.42   464.1 1576.61   469.1  1576.8     479  1579.6   518.8 1595.35
   548.6 1613.07   568.5 1623.54   628.9 1649.34   679.5 1667.93   760.4 1695.12
   790.7 1707.82     821  1722.5   841.2 1733.73   871.6 1753.93     912 1782.84
#Mann= 3 , 0 , 0
       0     .06       0   454.1    .045       0   464.1     .08       0
Bank Sta=454.1,464.1
XS Rating Curve= 0 ,0
Exp/Cntr=0.3,0.1

Type RM Length L Ch R = 1 ,3887.6  ,306.8,315.6,324.4
XS GIS Cut Line= 4
     1806437.743      127540.223     1806424.336      127253.312
     1806279.539      126971.763     1806274.176      126674.126
#Sta/Elev= 30
     9.9 1793.23    69.3 1754.38   108.9 1726.68   188.2 1672.02   267.4 1618.23
   287.2 1605.25   316.9 1587.12   326.8 1581.65   336.7 1578.09   346.6 1576.44
   376.3 1574.52   435.6 1567.61   445.5 1566.53   450.4 1566.41   455.4 1566.28
   460.4 1566.93   465.3 1567.58   475.2 1571.25     495 1580.17   643.5 1643.28
   673.3 1652.85   693.1 1660.25   722.9  1672.5   752.7 1685.54   792.4 1704.86
     842 1730.05   851.9 1735.72   871.7 1748.33   881.7 1754.98   901.5 1769.15
#Mann= 3 , 0 , 0
       0     .06       0   450.4    .045       0   460.4      .1       0
Bank Sta=450.4,460.4
XS Rating Curve= 0 ,0
Exp/Cntr=0.3,0.1

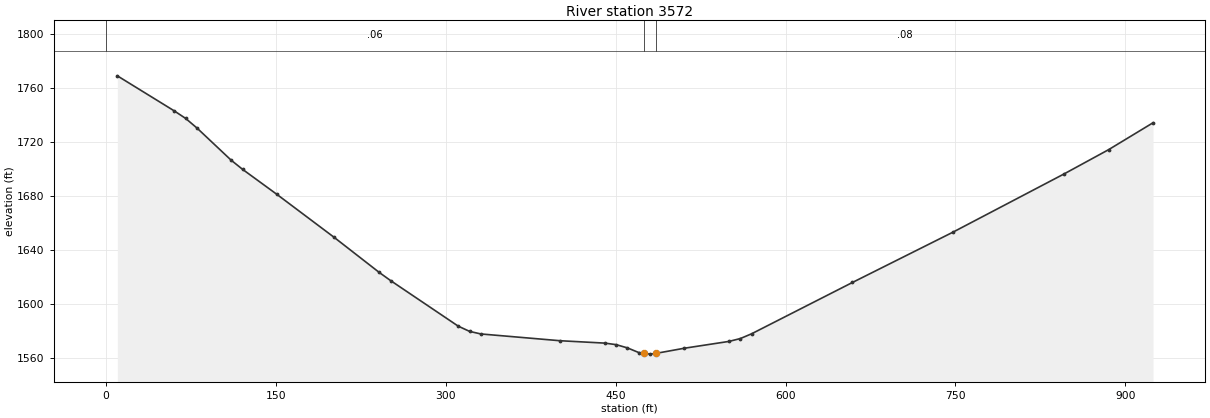
Type RM Length L Ch R = 1 ,3572    ,3563.8,3572,3577.1
XS GIS Cut Line= 4
     1806633.205      127530.049     1806665.663      127290.852
     1806649.574      126912.772     1806554.316      126623.307
#Sta/Elev= 30
    10.1 1768.92    60.3 1742.95    70.4 1737.35    80.5 1730.15   110.6 1706.36
   120.7 1699.57   150.9 1681.08   201.2 1649.37   241.4 1623.11   251.3 1617.14
   311.1 1583.31   321.1 1579.45     331 1577.55   400.7 1572.54   440.6 1570.75
   450.5 1569.61   460.5  1567.2   470.4 1563.78   475.4 1563.18   480.4 1562.59
   485.4  1563.1   510.3 1566.91   550.1 1572.02   560.1 1574.13     570 1577.64
   659.1 1615.72   747.6 1652.91   845.9 1696.17   885.2 1714.15   924.5 1734.13
#Mann= 3 , 0 , 0
       0     .06       0   475.4    .045       0   485.4     .08       0
Bank Sta=475.4,485.4
XS Rating Curve= 0 ,0
Exp/Cntr=0.3,0.1

Chan Stop Cuts=-1
Use User Specified Reach Order=0